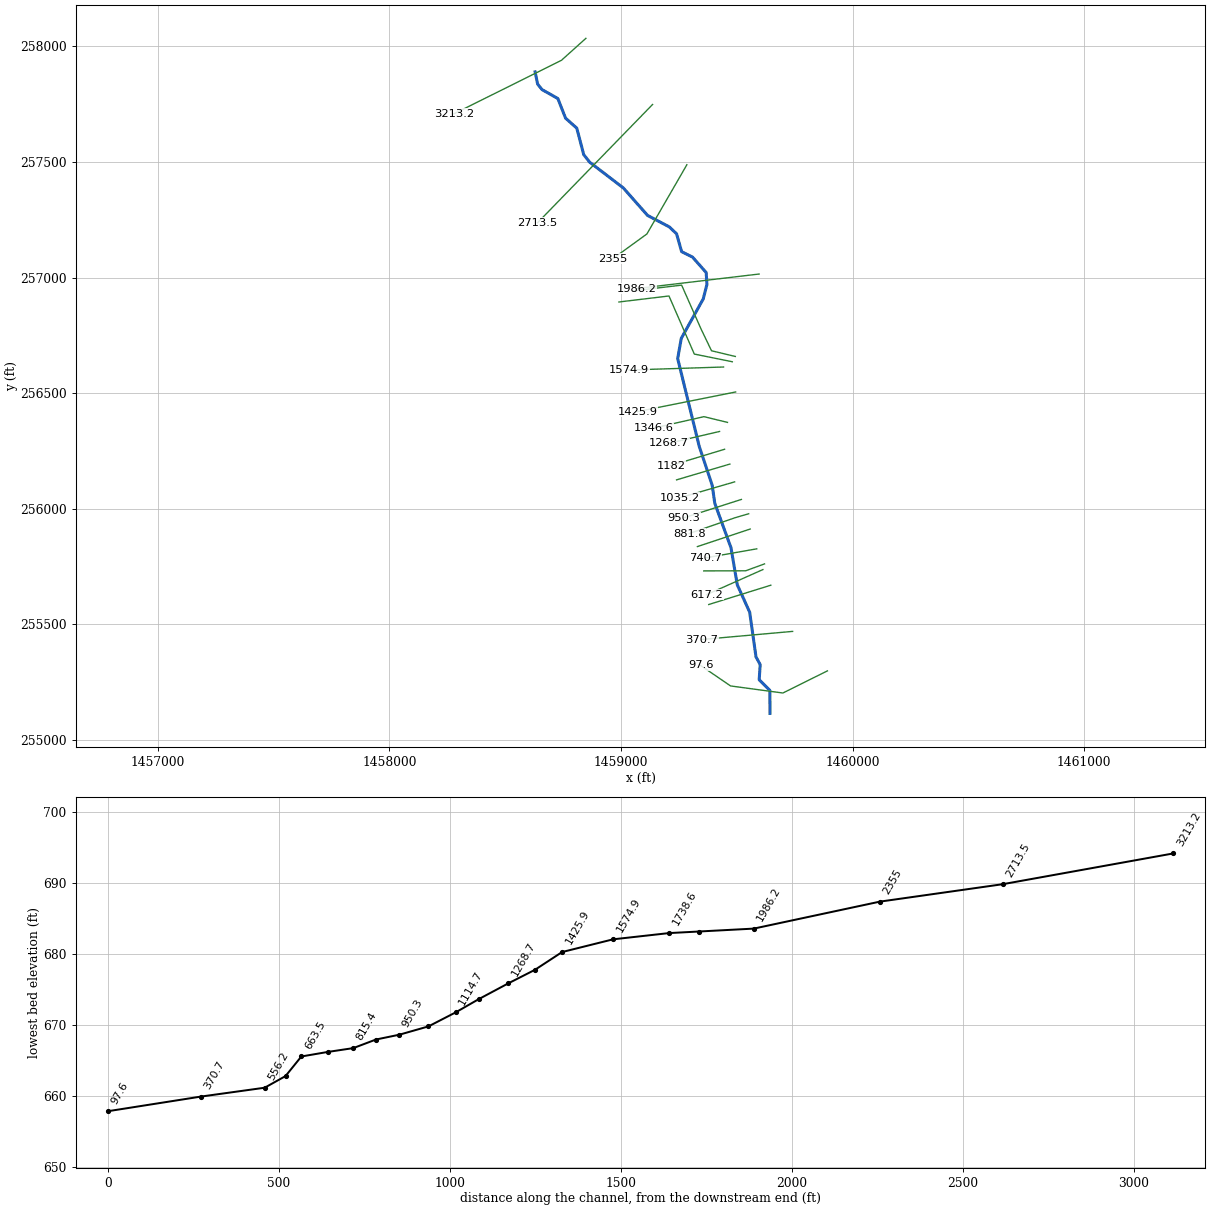
--- LRLRN1.prj (project) ---

Proj Title=LRLRN1
Current Plan=p01
Default Exp/Contr=0,0
English Units
Geom File=g01
Flow File=f01
Plan File=p01
BEGIN DESCRIPTION:
END DESCRIPTION:
DSS Export Rating Curves= 0
DSS Export Rating Curve Sorted= 0
DSS Export Volume Flow Curves= 0
DXF OffsetX= 0
DXF OffsetY= 0
DXF ScaleX= 0
DXF ScaleY= 0

--- LRLRN1.p01 (plan) ---

Plan Title=Floodplain
Program Version=4.00
Geom File=g01
Flow File=f01
K Sum by GR=0
Std Step Tol=0.01
Critical Tol=0.01
Num of Std Step Trials=20
Max Error Tol=0.3
Flow Tol Ratio=0.001
Split Flow NTrial=30
Split Flow Tol=0.02
Split Flow Ratio=0.02
Log Output Level=0
Friction Slope Method=1
Unsteady Friction Slope Method=2
Unsteady Bridges Friction Slope Method=1
Global Log Level=0
CheckData=False
Run HTab=0
Run UNet=0
Run PostProcess=0
UNET Theta=0
UNET Theta Warmup=0
UNET ZTol=0
UNET ZSATol=0
UNET MxIter=0
UNET MaxInSteps=0
UNET DtIC=0
UNET DtMin=0
UNET MaxCRTS=0
UNET WFStab=0
UNET SFStab=0
UNET WFX=0
UNET SFX=0
UNET DSS MLevel=0
UNET DZMax Abort=0
UNET Convert EG Bridges=0
UNET Use Existing IB Tables=0
UNET Froude Limit=0
UNET Froude Power=0
Write IC File=0
Echo Input=False
Echo Output=False
Write Detailed=0

--- LRLRN1.f01 (steady flow) ---

Flow Title=NFF Regression Equation
Program Version=4.10
Number of Profiles= 1
Profile Names=P100yr
River Rch & RM=LRLRN1,Main            ,3213.2
1086.484
River Rch & RM=LRLRN1,Main            ,881.8
1177.727
River Rch & RM=LRLRN1,Main            ,556.2
 1181.12
Boundary for River Rch & Prof#=LRLRN1,Main            , 1
Up Type= 0
Dn Type= 3
Dn Slope=0.007
DSS Import GetInterval= 0
DSS Import GetPeak= 0
DSS Import FillOption= 0

--- LRLRN1.g01 (geometry) ---

Geom Title=USGS 10m DEM
Program Version=4.10

River Reach=LRLRN1          ,Main
Reach XY= 30
     1458629.112      257889.793     1458640.059      257836.671
     1458659.117       257812.93     1458727.238      257774.477
     1458760.575       257689.43     1458809.062      257646.153
      1458839.03      257531.527     1458865.251      257498.562
     1459009.845      257387.682     1459114.732      257268.561
      1459208.38      257219.114     1459239.846      257189.147
     1459261.572       257111.98     1459308.774       257088.38
     1459367.524      257021.697     1459371.011      256970.328
     1459354.675      256906.775     1459260.176      256737.076
     1459244.625      256649.529     1459337.867       256268.76
     1459393.636      256100.905     1459404.807      256023.218
     1459474.853      255830.729     1459501.879      255670.781
     1459555.379      255552.199     1459582.784      255358.421
     1459600.842      255325.492      1459596.46      255259.984
       1459642.8      255213.427     1459643.002      255114.402

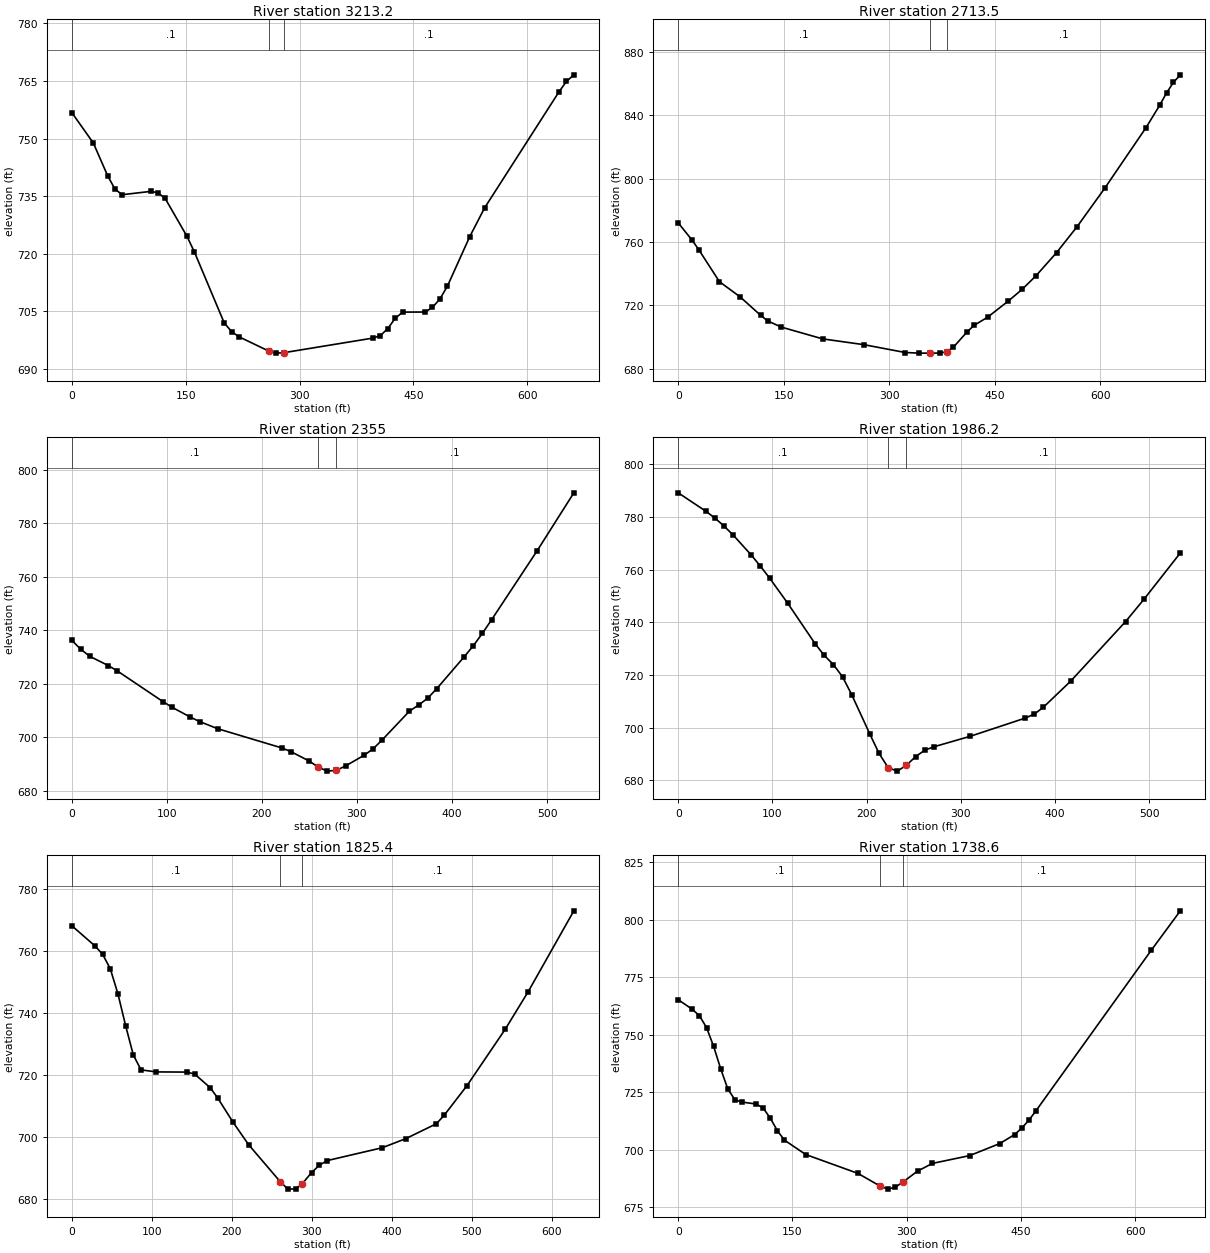
Type RM Length L Ch R = 1 ,3213.2  ,489.6,499.7,506.6
XS GIS Cut Line= 3
     1458848.281      258034.819     1458742.812      257939.767
     1458277.969      257707.996
#Sta/Elev= 30
       0  756.79    28.4  748.86    47.3  740.31    56.8  736.89    66.3  735.39
   104.1  736.26   113.6   735.9     123  734.43   151.8  724.54   161.6  720.46
   200.8  702.02   210.6  699.73   220.4  698.39   259.6  694.66   269.4  694.14
   279.2  694.25   396.8  698.06   406.6  698.72   416.4  700.55   426.2  703.25
     436  704.82   465.4  704.84   475.2  706.06     485  708.25   494.8  711.56
   524.2  724.45   543.8  731.95   641.8  762.18   651.6  764.88   661.4  766.61
#Mann= 3 , 0 , 0
       0      .1       0   259.6    .045       0   279.2      .1       0
Bank Sta=259.6,279.2
XS Rating Curve= 0 ,0
Exp/Cntr=0.3,0.1

Type RM Length L Ch R = 1 ,2713.5  ,352.2,358.5,364.7
XS GIS Cut Line= 2
     1459136.193      257748.686     1458639.232      257236.534
#Sta/Elev= 30
       0  772.11    19.6  761.27    29.3  755.11    58.6  734.93      88  725.34
   117.3  713.63   127.1  710.17   146.6  706.24   205.3   698.8     264  695.14
   322.6  690.19   342.2   689.8  357.38   689.8   371.5  689.83   381.3  690.59
     391   693.5   410.6  703.25   420.4  707.33   439.9  712.56   469.2  722.75
   488.8  730.13   508.3   738.6   537.7  753.32     567   769.8   606.1  793.96
   664.8  832.28   684.3  846.46   694.1  854.34   703.9  860.96   713.6   865.7
#Mann= 3 , 0 , 0
       0      .1       0  357.38    .045       0   381.3      .1       0
Bank Sta=357.38,381.3
XS Rating Curve= 0 ,0
Exp/Cntr=0.3,0.1

Type RM Length L Ch R = 1 ,2355    ,391.8,368.8,345.7
XS GIS Cut Line= 3
     1459284.305      257487.999     1459111.779      257188.519
      1458964.21      257081.098
#Sta/Elev= 30
       0  736.28     9.6  732.87    19.2  730.23    38.4  726.84      48   724.8
      96  713.33   105.6  711.21   124.8  707.54   134.4   705.9   153.6   703.2
   220.8  696.04   230.4  694.67   249.6  691.16   259.2  688.87   268.8  687.35
   278.4  687.66     288  689.29   307.2  693.21   316.8  695.62   326.4  698.96
   355.2  709.77   364.8  712.05   374.4   714.6     384   718.2   412.9  730.14
   422.5  734.27   432.1  738.94   441.7  743.98   489.7  769.83   528.2  791.43
#Mann= 3 , 0 , 0
       0      .1       0   259.2    .045       0   278.4      .1       0
Bank Sta=259.2,278.4
XS Rating Curve= 0 ,0
Exp/Cntr=0.3,0.1

Type RM Length L Ch R = 1 ,1986.2  ,196.6,160.8,127
XS GIS Cut Line= 2
     1459596.263       257015.18     1459066.749      256952.246
#Sta/Elev= 30
       0  789.08    29.1  782.15    38.8  779.55    48.5  776.52    58.2  773.12
    77.6  765.48    87.3  761.25      97  756.76   116.3   747.2   145.4  731.84
   155.1  727.42   164.8  723.95   174.5   719.3   184.2  712.56   203.6  697.52
   213.3  690.24     223  684.84   232.7  683.55   242.4  685.79   252.1  689.06
   261.8  691.48   271.5  692.78   310.2  696.77   368.4  703.65   378.1  705.16
   387.8  707.78   416.9  717.72   475.1  740.27   494.5  748.67   533.2  766.28
#Mann= 3 , 0 , 0
       0      .1       0     223    .045       0   242.4      .1       0
Bank Sta=223,242.4
XS Rating Curve= 0 ,0
Exp/Cntr=0.3,0.1

Type RM Length L Ch R = 1 ,1825.4  ,86.1,86.8,86
XS GIS Cut Line= 5
     1459493.485      256658.474      1459390.62      256683.213
     1459345.048      256778.265     1459261.714      256967.068
     1459053.381      256942.328
#Sta/Elev= 30
       0  768.18    28.8  761.69    38.5  758.97    48.1  754.29    57.7  746.16
    67.3  735.91    76.9  726.43    86.6  721.63   105.8  720.98   144.1  720.92
   153.7  720.25   172.9  715.91   182.5   712.5   201.6  704.71     221  697.48
   260.4  685.57   270.1  683.14     280  683.23   287.6  684.76   299.7  688.48
   309.5  690.89   319.3  692.36   388.1  696.51   417.6  699.46   455.7  704.26
   465.3  706.96   493.9  716.56   541.6  734.73   570.2  746.82   627.4  772.98
#Mann= 3 , 0 , 0
       0      .1       0   260.4    .045       0   287.6      .1       0
Bank Sta=260.4,287.6
XS Rating Curve= 0 ,0
Exp/Cntr=0.3,0.1

Type RM Length L Ch R = 1 ,1738.6  ,130.8,163.8,196.1
XS GIS Cut Line= 4
     1459480.462      256635.631     1459316.402       256668.89
     1459207.027      256920.193     1458990.881      256894.151
#Sta/Elev= 30
       0  765.23    18.6  761.02    27.9  758.23    37.2  753.08    46.5  744.93
    55.8  735.12    65.1  726.45    74.4  721.75    83.7  720.75   102.3  719.91
   111.6  718.12   120.9  713.73   130.2  708.29   139.5  704.19   167.4  697.96
   235.9  689.76   265.3   684.2   275.1  682.92   284.9  683.74   294.6   685.9
   314.2  690.75   333.8   694.1   382.7  697.49   421.9  702.69   441.5  706.58
   450.9  709.39   460.4  712.88   469.9  717.07   621.3  786.82   659.2  803.85
#Mann= 3 , 0 , 0
       0      .1       0   265.3    .045       0   294.6      .1       0
Bank Sta=265.3,294.6
XS Rating Curve= 0 ,0
Exp/Cntr=0.3,0.1

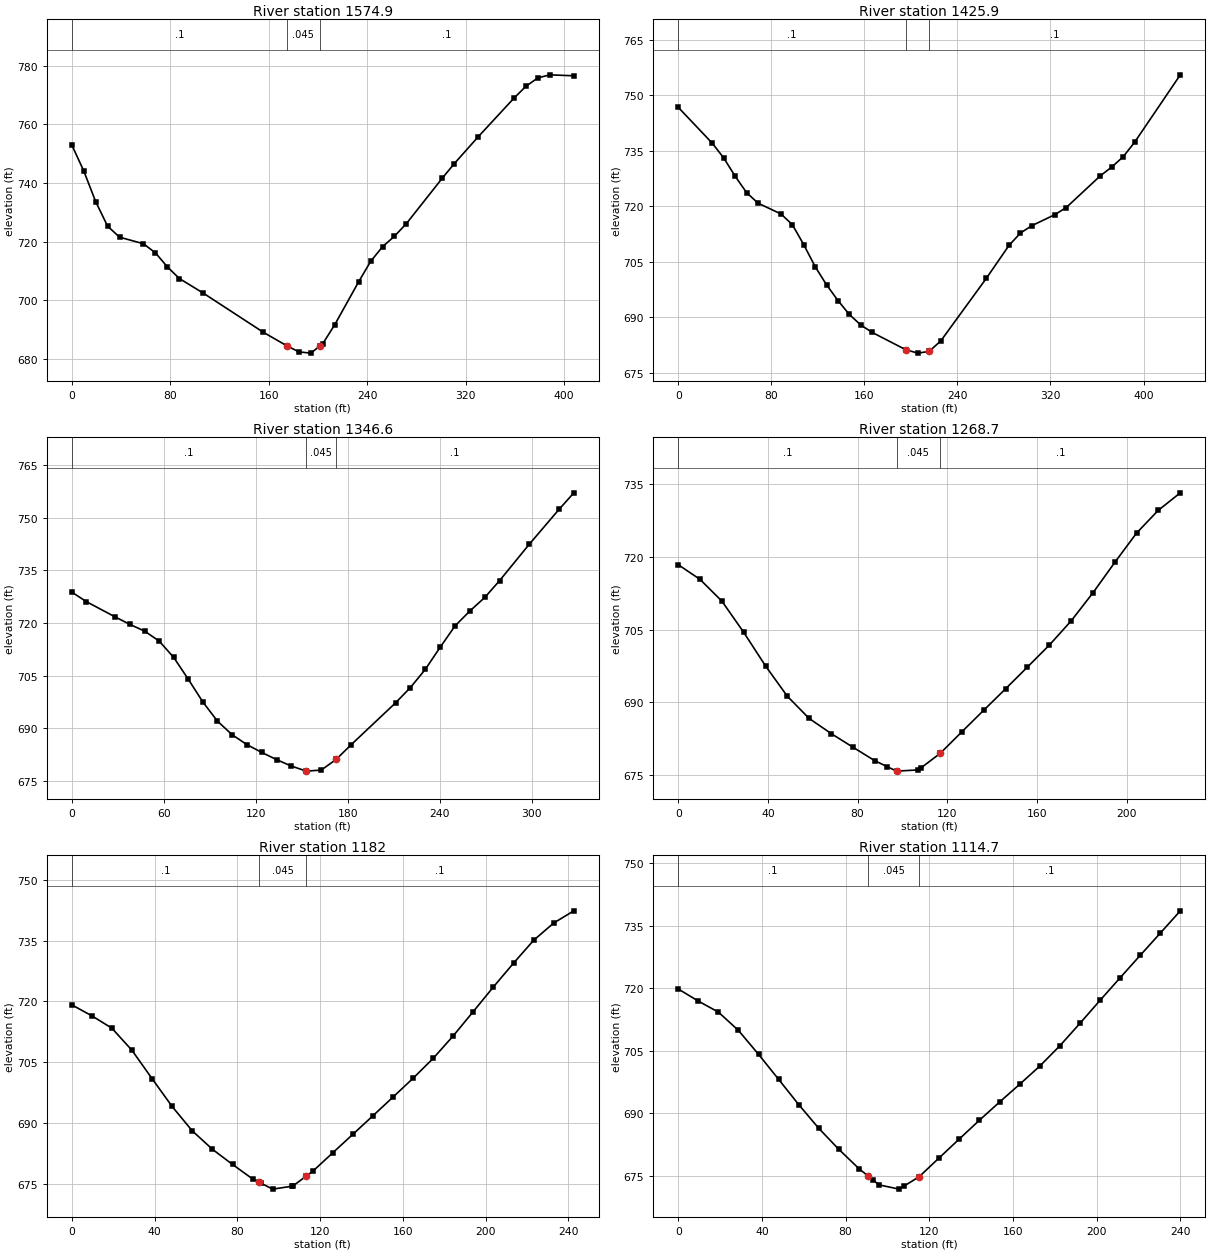
Type RM Length L Ch R = 1 ,1574.9  ,144.8,149,153.1
XS GIS Cut Line= 2
     1459442.704      256612.901     1459035.152       256599.88
#Sta/Elev= 30
       0  752.96     9.7  744.14    19.4  733.66    29.1  725.29    38.8  721.54
    58.2  719.29      68  716.18    77.7  711.39    87.4  707.45   106.8  702.48
   155.3  689.22   174.8   684.5   184.5  682.46   194.2  682.04   201.5684.4717
   203.9  685.27   213.6  691.72     233  706.33   242.7  713.26   252.4  718.27
   262.1  721.87   271.8  726.16     301  741.66   310.7  746.59   330.1  755.72
   359.2   768.9   368.9  772.94   378.6  775.79   388.3  776.83   407.8   776.5
#Mann= 3 , 0 , 0
       0      .1       0   174.8    .045       0   201.5      .1       0
Bank Sta=174.8,201.5
XS Rating Curve= 0 ,0
Exp/Cntr=0.3,0.1

Type RM Length L Ch R = 1 ,1425.9  ,78.6,79.3,79.9
XS GIS Cut Line= 2
     1459494.787      256504.828      1459071.61      256420.193
#Sta/Elev= 30
       0  746.78    29.4  737.02    39.2  733.02      49   728.1    58.8  723.67
    68.7  720.82    88.3  717.92    98.1  715.02   107.9   709.6   117.7  703.66
   127.5  698.73   137.3  694.49   147.1  690.71   156.9  687.87   166.7  685.86
   195.6681.1663     206  680.25   215.6680.7103   225.6  683.52   264.8  700.47
   284.4  709.43   294.2  712.76     304  714.75   323.7  717.72   333.5  719.64
   362.9  728.26   372.7  730.62   382.5   733.4   392.3  737.32   431.6  755.57
#Mann= 3 , 0 , 0
       0      .1       0   195.6    .045       0   215.6      .1       0
Bank Sta=195.6,215.6
XS Rating Curve= 0 ,0
Exp/Cntr=0.3,0.1

Type RM Length L Ch R = 1 ,1346.6  ,77.8,78,78.1
XS GIS Cut Line= 3
     1459459.631      256373.318     1459358.068      256398.057
      1459140.62      256348.578
#Sta/Elev= 30
       0  728.78     9.5  726.07    28.5  721.66      38  719.56    47.5  717.66
      57  714.83    66.5  710.16      76  703.95    85.5  697.46      95  692.02
   104.5  688.16   114.2  685.32   123.9  683.08   133.6  681.03   143.3  679.18
     153  677.75   162.7  678.05   172.4  681.07   182.1  685.22   211.2  697.21
   220.9  701.58   230.6  706.75   240.3  713.06     250  719.14   259.7  723.41
   269.4  727.25   279.1  732.07   298.4  742.41   317.8  752.34   327.5  757.08
#Mann= 3 , 0 , 0
       0      .1       0     153    .045       0   172.4      .1       0
Bank Sta=153,172.4
XS Rating Curve= 0 ,0
Exp/Cntr=0.3,0.1

Type RM Length L Ch R = 1 ,1268.7  ,85,86.7,88.3
XS GIS Cut Line= 2
     1459425.343      256334.038     1459207.244       256283.04
#Sta/Elev= 26
       0  718.38     9.7  715.36    19.5  710.86    29.2  704.45      39  697.48
    48.7  691.26    58.4   686.7    68.2  683.59    77.9  680.78    87.6  678.01
    93.1  676.79    97.4  675.84   107.1  676.09   108.1  676.44   116.9  679.51
   126.6  683.97   136.3  688.39   146.1  692.83   155.8  697.29   165.6  701.83
   175.3   706.8     185  712.57   194.8  718.87   204.5  724.91   214.2   729.6
     224  733.19
#Mann= 3 , 0 , 0
       0      .1       0    97.4    .045       0   116.9      .1       0
Bank Sta=97.4,116.9
XS Rating Curve= 0 ,0
Exp/Cntr=0.3,0.1

Type RM Length L Ch R = 1 ,1182    ,67.4,67.3,67.1
XS GIS Cut Line= 2
     1459447.044      256256.998     1459214.839      256186.469
#Sta/Elev= 30
       0  719.13     9.7  716.42    19.4  713.36    29.1   707.9    38.8  700.91
    48.5  694.03    58.2  688.03      68  683.45    77.7  679.71    87.4  676.13
   90.48675.3292    91.4  675.09    97.1  673.61   106.4  674.32   106.8  674.35
  113.24676.7866   116.5  678.02   126.2   682.6   135.9  687.16   145.6  691.74
   155.3  696.35     165     701   174.7   705.9   184.4  711.47   194.1  717.48
   203.8  723.54   213.6  729.46   223.3  735.09     233  739.35   242.7  742.35
#Mann= 3 , 0 , 0
       0      .1       0   90.48    .045       0  113.24      .1       0
Bank Sta=90.48,113.24
XS Rating Curve= 0 ,0
Exp/Cntr=0.3,0.1

Type RM Length L Ch R = 1 ,1114.7  ,79.6,79.4,79.3
XS GIS Cut Line= 2
     1459469.831      256192.979     1459239.796       256124.62
#Sta/Elev= 29
       0  719.82     9.6   716.9    19.2  714.26    28.8  709.85    38.4  704.11
      48   698.1    57.6  692.04    67.2  686.34    76.8  681.29    86.4  676.66
    90.6674.9612    93.1  673.95      96  672.77   105.6  671.75   108.1  672.53
   115.2  674.74   124.8  679.29   134.4  683.81     144  688.31   153.6  692.66
   163.2  696.92   172.8  701.28   182.4  706.16     192  711.55   201.6  717.06
   211.2  722.49   220.8  727.87   230.4  733.21     240  738.58
#Mann= 3 , 0 , 0
       0      .1       0    90.6    .045       0   115.2      .1       0
Bank Sta=90.6,115.2
XS Rating Curve= 0 ,0
Exp/Cntr=0.3,0.1

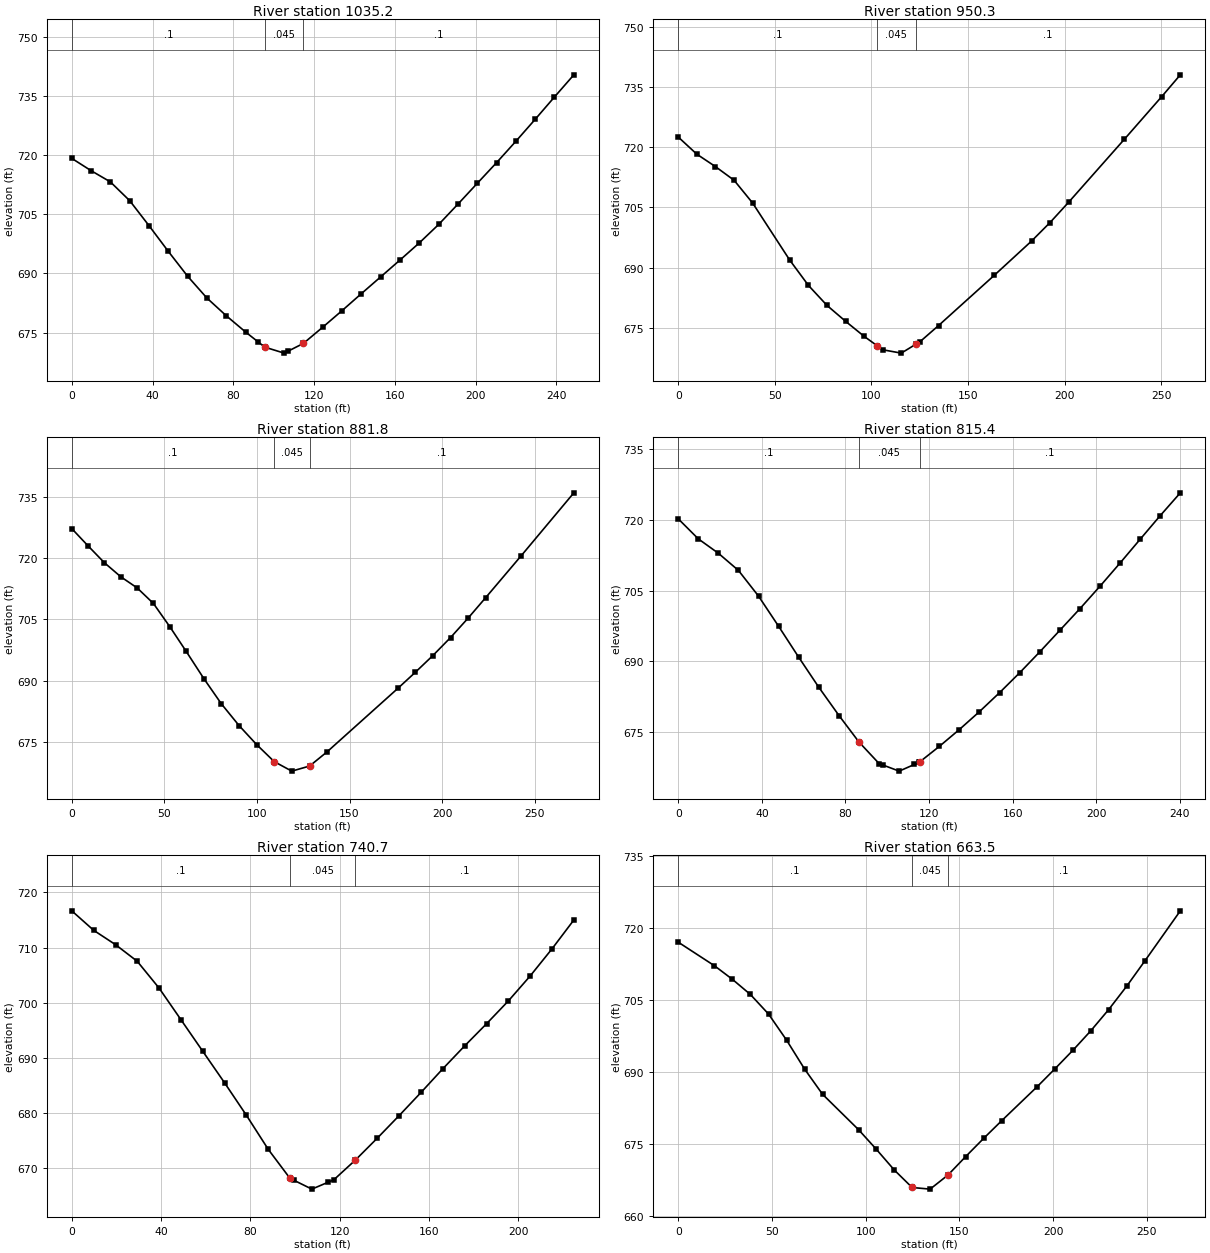
Type RM Length L Ch R = 1 ,1035.2  ,84.3,85,85.5
XS GIS Cut Line= 2
     1459490.447      256115.939     1459251.732      256046.495
#Sta/Elev= 29
       0  719.18     9.6  716.05    19.1  713.22    28.7  708.44    38.2  702.14
    47.8  695.59    57.4  689.26    66.9  683.76    76.5  679.26    86.1  675.12
    92.2  672.66    95.6  671.29   105.2  669.78   107.2   670.3   114.7  672.25
   124.3  676.37   133.9  680.59   143.4  684.87     153  689.14   162.6  693.43
   172.1  697.75   181.7  702.43   191.2  707.57   200.8  712.86   210.4  718.13
   219.9  723.52   229.5  729.11     239  734.75   248.6  740.37
#Mann= 3 , 0 , 0
       0      .1       0    95.6    .045       0   114.7      .1       0
Bank Sta=95.6,114.7
XS Rating Curve= 0 ,0
Exp/Cntr=0.3,0.1

Type RM Length L Ch R = 1 ,950.3   ,67.9,68.5,69
XS GIS Cut Line= 2
     1459519.744      256039.984     1459272.348      255960.774
#Sta/Elev= 23
       0   722.6     9.6  718.32    19.2  715.23    28.9   711.8    38.5  706.11
    57.7  691.85    67.4  685.51      77  680.52    86.6  676.56    96.2   672.8
   102.9670.4623   105.8  669.45   115.4  668.61   122.9670.8141   125.1  671.46
   134.7   675.5   163.6  688.08   182.8   696.6   192.4  701.24     202   706.3
   230.9  722.07   250.2  732.71   259.8  738.14
#Mann= 3 , 0 , 0
       0      .1       0   102.9    .045       0   122.9      .1       0
Bank Sta=102.9,122.9
XS Rating Curve= 0 ,0
Exp/Cntr=0.3,0.1

Type RM Length L Ch R = 1 ,881.8   ,66.7,66.4,66.1
XS GIS Cut Line= 3
     1459551.211      255978.135     1459491.988      255960.655
     1459294.049      255892.415
#Sta/Elev= 24
       0  727.22     8.8  722.99    17.6  718.88    26.5  715.43    35.3  712.72
    44.1  708.91    52.9  703.26    61.8  697.19    71.3  690.56    80.8  684.37
    90.3  679.08    99.8  674.43   109.3  670.26   118.8  667.93   128.4  669.17
   137.9  672.66     176  688.13   185.5  692.09     195  696.19   204.5  700.57
     214  705.33   223.5  710.34   242.6  720.54   271.1  735.96
#Mann= 3 , 0 , 0
       0      .1       0   109.3    .045       0   128.4      .1       0
Bank Sta=109.3,128.4
XS Rating Curve= 0 ,0
Exp/Cntr=0.3,0.1

Type RM Length L Ch R = 1 ,815.4   ,78.3,74.6,70.9
XS GIS Cut Line= 2
     1459557.721      255911.946     1459329.857      255835.991
#Sta/Elev= 29
       0  720.21     9.6  715.96    19.2  712.91    28.8  709.27    38.4  703.83
      48  697.44    57.6  690.89    67.2  684.53    76.9  678.51    86.5  672.87
    96.1  668.32      98     668   105.7  666.72     113  668.14   115.3  668.59
   115.5668.6602   124.9  671.96   134.5  675.54   144.1  679.33   153.7  683.34
   163.3  687.55   172.9  691.97   182.5  696.54   192.2  701.17   201.8  705.93
   211.4  710.85     221  715.88   230.6  720.89   240.2  725.72
#Mann= 3 , 0 , 0
       0      .1       0    86.5    .045       0   115.5      .1       0
Bank Sta=86.5,115.5
XS Rating Curve= 0 ,0
Exp/Cntr=0.3,0.1

Type RM Length L Ch R = 1 ,740.7   ,81.5,77.2,72.9
XS GIS Cut Line= 2
     1459585.933      255826.226     1459364.579      255787.163
#Sta/Elev= 26
       0  716.67     9.8  713.14    19.6  710.53    29.3  707.52    39.1  702.65
    48.9  696.91    58.6  691.22    68.4  685.48    78.2  679.57      88  673.38
    97.7  668.14    99.6  667.76   107.5  666.18   114.6   667.4   117.3  667.86
     127  671.46   136.8  675.43   146.6  679.53   156.4  683.73   166.1     688
   175.9  692.16   185.7  696.18   195.5  700.33   205.2  704.83     215  709.76
   224.8  715.01
#Mann= 3 , 0 , 0
       0      .1       0    97.7    .045       0     127      .1       0
Bank Sta=97.7,127
XS Rating Curve= 0 ,0
Exp/Cntr=0.3,0.1

Type RM Length L Ch R = 1 ,663.5   ,36,46.3,56.9
XS GIS Cut Line= 3
      1459619.57      255761.121     1459538.193      255731.298
     1459356.983      255730.739
#Sta/Elev= 25
       0  717.06    19.3  712.15    28.9  709.31    38.5  706.15    48.2  702.06
    57.8  696.63    67.4   690.6      77  685.33    96.2  677.95   105.7  673.85
   115.3  669.52   124.8  665.88   134.4  665.54   143.9  668.47   153.4  672.34
     163  676.14   172.5  679.78   191.6  686.94   201.1  690.68   210.7  694.55
   220.2   698.6   229.7  703.01   239.3  707.88   248.8  713.05   267.9   723.6
#Mann= 3 , 0 , 0
       0      .1       0   124.8    .045       0   143.9      .1       0
Bank Sta=124.8,143.9
XS Rating Curve= 0 ,0
Exp/Cntr=0.3,0.1

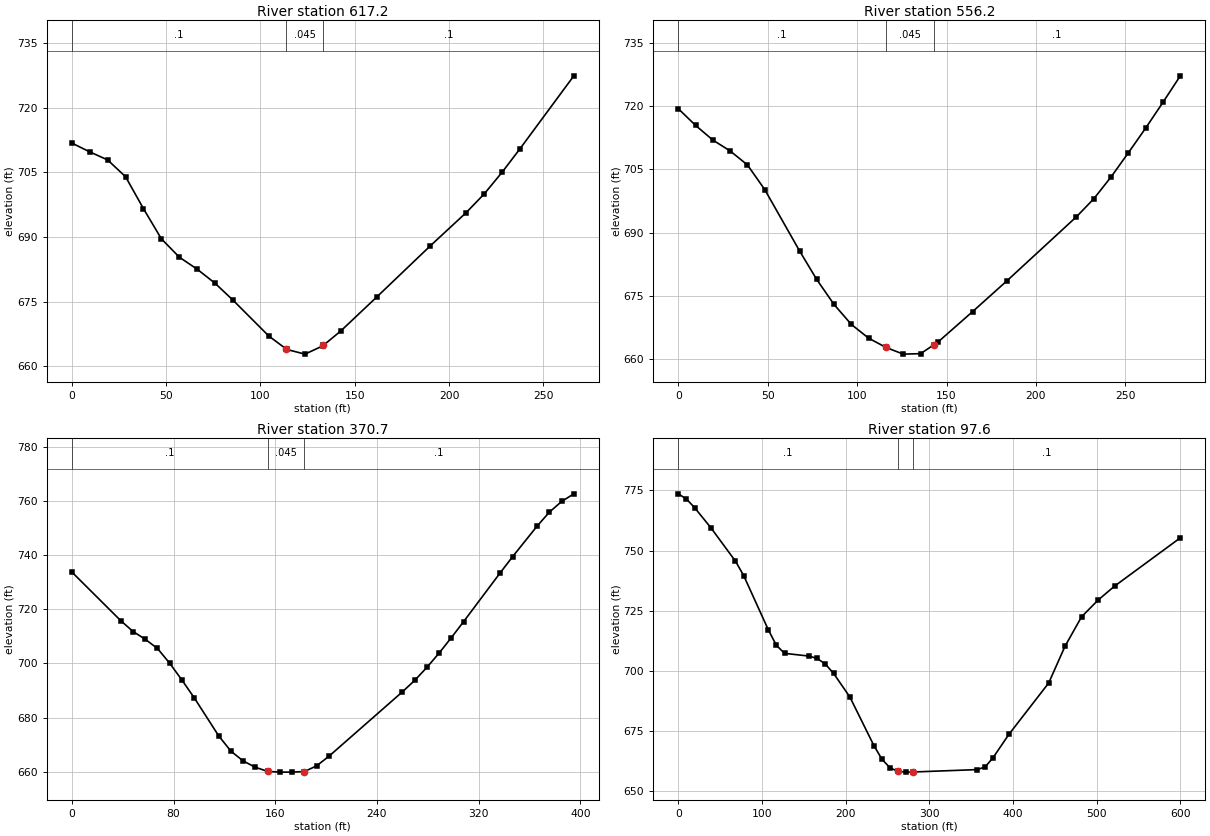
Type RM Length L Ch R = 1 ,617.2   ,63.4,61,57.5
XS GIS Cut Line= 2
     1459612.409      255736.469     1459369.353      255628.135
#Sta/Elev= 24
       0  711.85     9.5   709.8      19  707.92    28.5  704.02      38  696.59
    47.5  689.58      57  685.32    66.5  682.51      76  679.23    85.5   675.3
   104.5  666.96   113.4664.0558     114  663.86   123.6  662.78     133  664.69
   133.4 664.835   142.6  668.17   161.6  676.04   190.1  687.98   209.1   695.7
   218.6  700.02   228.1  705.07   237.6  710.54   266.1  727.47
#Mann= 3 , 0 , 0
       0      .1       0   113.4    .045       0   133.4      .1       0
Bank Sta=113.4,133.4
XS Rating Curve= 0 ,0
Exp/Cntr=0.3,0.1

Type RM Length L Ch R = 1 ,556.2   ,190.8,185.5,180
XS GIS Cut Line= 2
     1459646.697       255668.89     1459378.685       255585.34
#Sta/Elev= 25
       0   719.4     9.7  715.42    19.4  711.93      29  709.37    38.7  706.04
    48.4  700.17    67.8  685.66    77.4  678.87    87.1  672.93    96.8  668.18
   106.5  664.91   116.2  662.72   125.8  661.14   135.5  661.25   142.8663.3192
   145.2     664   164.6  671.24   183.9  678.59   222.6  693.73   232.3  697.99
     242   703.2   251.7  708.95   261.4  714.83     271   720.9   280.7  727.19
#Mann= 3 , 0 , 0
       0      .1       0   116.2    .045       0   142.8      .1       0
Bank Sta=116.2,142.8
XS Rating Curve= 0 ,0
Exp/Cntr=0.3,0.1

Type RM Length L Ch R = 1 ,370.7   ,277.3,273.2,257
XS GIS Cut Line= 2
     1459740.794      255469.064     1459347.565      255433.908
#Sta/Elev= 30
       0  733.79    38.5  715.81    48.2   711.8    57.8  708.93    67.4  705.54
      77  700.09    86.7  693.84    96.3  687.33   115.6  673.24   125.2  667.62
   134.8  664.02   144.4  661.68   154.1  660.16   163.7  659.91   173.3   659.9
     183  660.12   192.6  662.24   202.2  665.75     260  689.54   269.6  693.73
   279.2  698.53   288.9  703.87   298.5  709.55   308.1  715.44     337  733.53
   346.6   739.4   365.9   750.7   375.5  755.83   385.2   759.8   394.8  762.62
#Mann= 3 , 0 , 0
       0      .1       0   154.1    .045       0     183      .1       0
Bank Sta=154.1,183
XS Rating Curve= 0 ,0
Exp/Cntr=0.3,0.1

Type RM Length L Ch R = 1 ,97.6    ,94.1,97.6,111.2
XS GIS Cut Line= 4
      1459891.12      255298.328     1459698.758      255202.495
     1459473.064      255233.051     1459343.203       255321.94
#Sta/Elev= 30
       0  773.59     9.8  771.43    19.5  767.86    39.1  759.44    68.4  745.57
    78.2   739.6   107.5  717.14   117.2  710.62     127  707.24   156.3   706.1
   166.1  705.12   175.8  702.76   185.6  698.93   205.1  689.08   233.9  668.82
   243.4  663.22   252.9  659.68   262.4  658.16   271.8  657.83   280.7657.8862
   357.3  658.88   366.8     660   376.2  663.82   395.2  673.56   442.7   694.9
   462.3  710.25     482  722.44   501.7  729.38   521.4  735.19     600  755.28
#Mann= 3 , 0 , 0
       0      .1       0   262.4    .045       0   280.7      .1       0
Bank Sta=262.4,280.7
XS Rating Curve= 0 ,0
Exp/Cntr=0.3,0.1

Chan Stop Cuts=-1
Use User Specified Reach Order=0
Composite Channel Slope=5